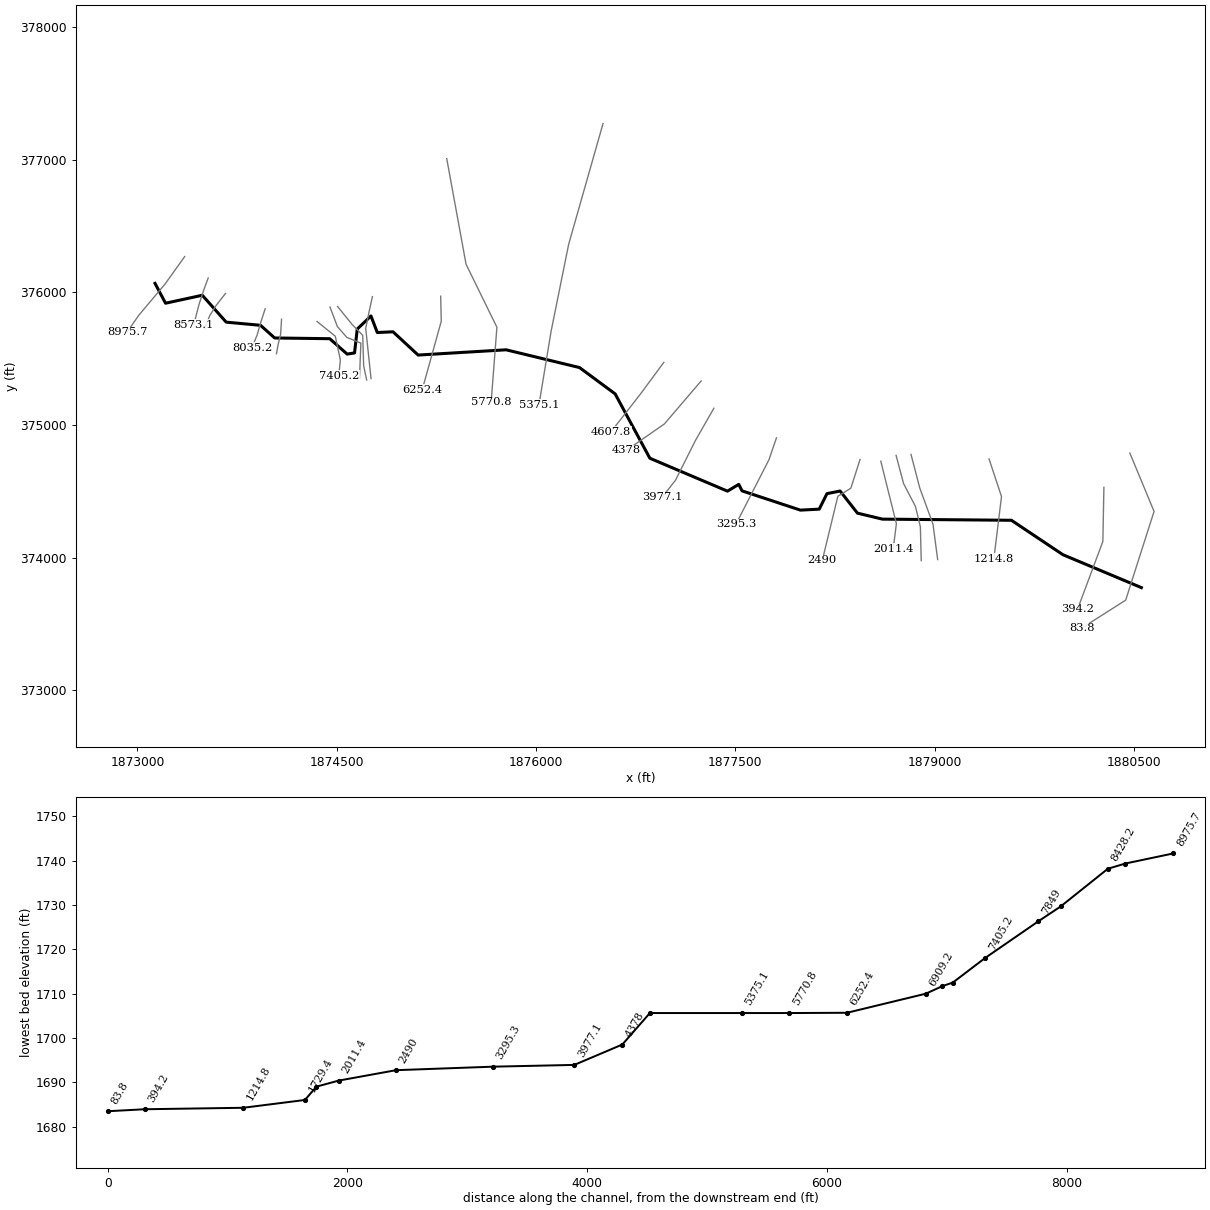
--- LAURELRN2.prj (project) ---

Proj Title=LAURELRN2
Current Plan=p01
Default Exp/Contr=0,0
English Units
Geom File=g01
Flow File=f01
Plan File=p01
BEGIN DESCRIPTION:
END DESCRIPTION:
DSS Export Rating Curves= 0
DSS Export Rating Curve Sorted= 0
DSS Export Volume Flow Curves= 0
DXF OffsetX= 0
DXF OffsetY= 0
DXF ScaleX= 0
DXF ScaleY= 0

--- LAURELRN2.p01 (plan) ---

Plan Title=Floodplain
Program Version=4.00
Geom File=g01
Flow File=f01
K Sum by GR=0
Std Step Tol=0.01
Critical Tol=0.01
Num of Std Step Trials=20
Max Error Tol=0.3
Flow Tol Ratio=0.001
Split Flow NTrial=30
Split Flow Tol=0.02
Split Flow Ratio=0.02
Log Output Level=0
Friction Slope Method=1
Unsteady Friction Slope Method=2
Unsteady Bridges Friction Slope Method=1
Global Log Level=0
CheckData=False
Run HTab=0
Run UNet=0
Run PostProcess=0
UNET Theta=0
UNET Theta Warmup=0
UNET ZTol=0
UNET ZSATol=0
UNET MxIter=0
UNET MaxInSteps=0
UNET DtIC=0
UNET DtMin=0
UNET MaxCRTS=0
UNET WFStab=0
UNET SFStab=0
UNET WFX=0
UNET SFX=0
UNET DSS MLevel=0
UNET DZMax Abort=0
UNET Convert EG Bridges=0
UNET Use Existing IB Tables=0
UNET Froude Limit=0
UNET Froude Power=0
Write IC File=0
Echo Input=False
Echo Output=False
Write Detailed=0

--- LAURELRN2.f01 (steady flow) ---

Flow Title=NFF Regression Equation
Program Version=4.00
Number of Profiles=1
Profile Names=P100yr
River Rch & RM=LAURELRN2,Main      ,8975.7
  915.42
River Rch & RM=LAURELRN2,Main      ,6909.2
  978.76
River Rch & RM=LAURELRN2,Main      ,3977.1
1072.298
River Rch & RM=LAURELRN2,Main      ,83.8
 1146.15
Boundary for River Rch & Prof#=LAURELRN2,Main      ,1
Up Type=0
Dn Type=3
Dn Slope=0.001755

--- LAURELRN2.g01 (geometry) ---

Geom Title=USGS 10m DEM
Program Version=4.10

River Reach=LAURELRN2       ,Main
Reach XY= 30
     1873132.222      376067.948      1873211.57      375918.065
     1873488.218       375978.17     1873667.897      375775.356
     1873926.586       375751.39     1874032.923      375655.904
     1874447.419      375650.479     1874578.713      375534.376
     1874634.051      375543.057     1874654.667      375723.178
     1874757.685      375822.065     1874805.492      375697.137
     1874923.765      375702.562     1875112.884      375527.044
      1875775.11      375566.711     1876327.764      375432.704
     1876595.817      375234.276     1876857.098      374748.786
     1877441.299      374500.522     1877526.369      374551.737
     1877551.193      374502.664     1877990.238      374357.482
     1878131.922      374364.643     1878190.516       374481.83
     1878289.475      374501.362     1878419.683      374334.695
     1878607.737      374289.454     1879578.875      374280.774
     1879966.124      374021.327     1880556.956      373772.961

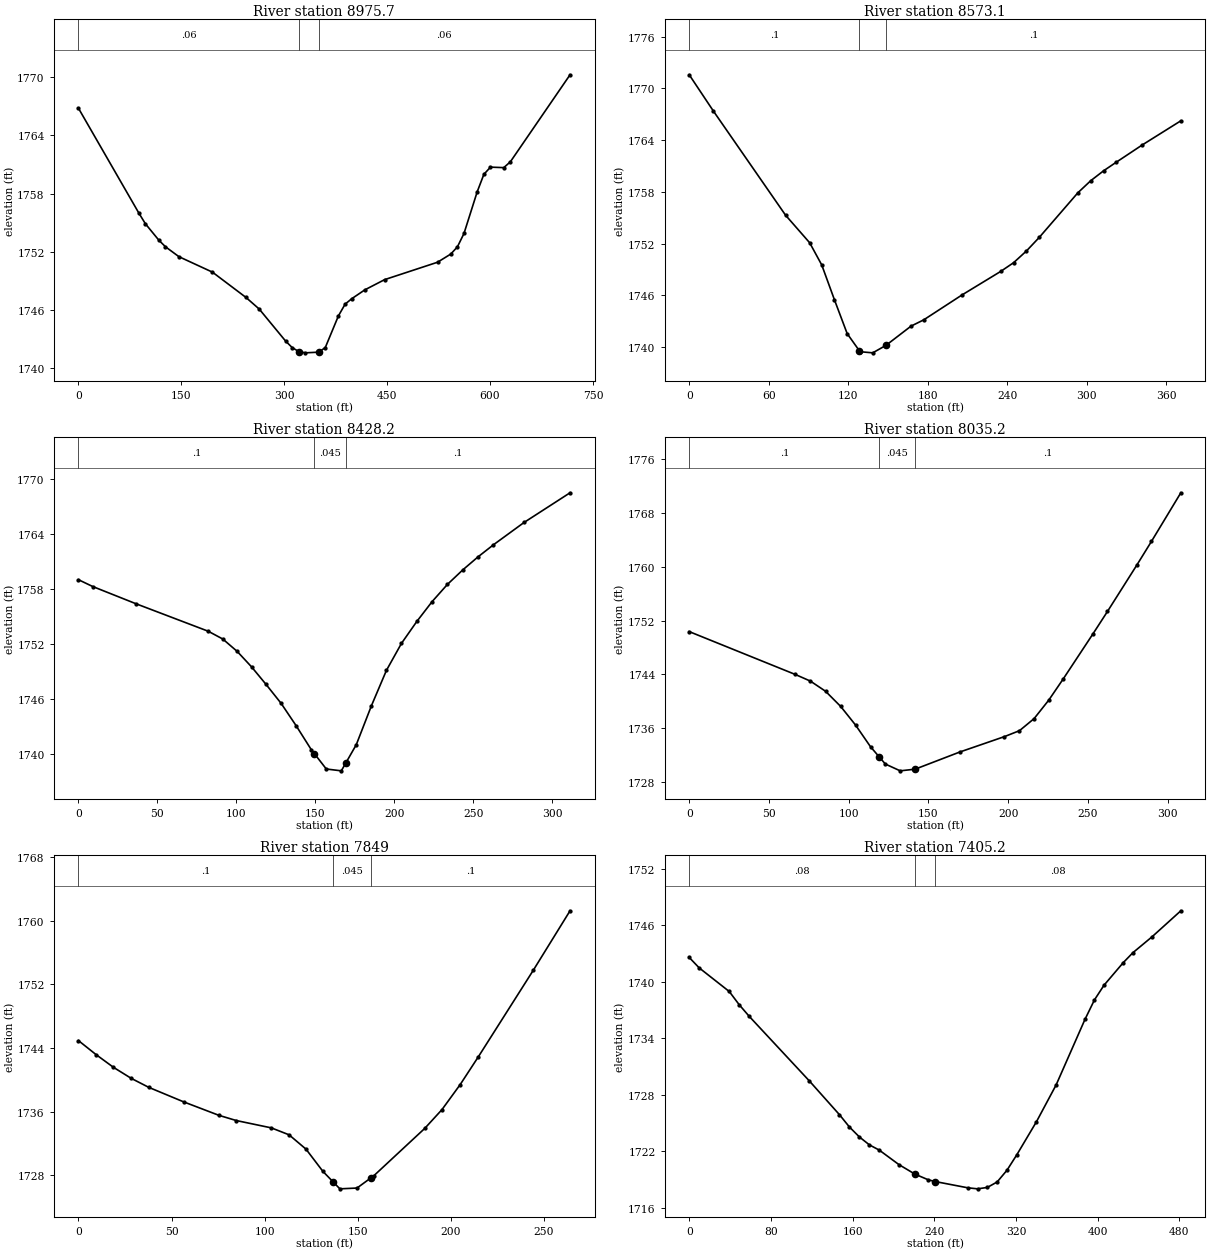
Type RM Length L Ch R = 1 ,8975.7  ,398.6,402.6,401.3
XS GIS Cut Line= 4
     1873355.538      376269.778     1873207.969      376063.181
     1873010.052       375827.07     1872921.511      375700.334
#Sta/Elev= 30
       0  1766.8    87.9 1756.02    97.6  1754.9   117.2 1753.21   126.9 1752.53
   146.5 1751.51   195.3 1749.92   244.1 1747.32   263.5 1746.12     302 1742.82
   311.6 1742.15   321.3 1741.74   330.9 1741.61   350.2 1741.68   359.8 1742.15
     379 1745.42   388.7 1746.62   398.3 1747.18   417.6  1748.1   446.4 1749.15
   523.5 1750.94   542.7 1751.78   552.4 1752.52     562  1753.9   581.3  1758.2
     591 1759.99   600.6 1760.73     620 1760.68   629.6 1761.28   716.6 1770.24
#Mann= 3 , 0 , 0
       0     .06       0   321.3    .045       0   350.2     .06       0
Bank Sta=321.3,350.2
XS Rating Curve= 0 ,0
Exp/Cntr=0.3,0.1

Type RM Length L Ch R = 1 ,8573.1  ,151,145,142.2
XS GIS Cut Line= 4
     1873532.622       376108.32       1873497.9       376014.57
     1873464.913      375913.876     1873423.247      375754.153
#Sta/Elev= 24
       0 1771.58    18.2 1767.38    72.7 1755.29    90.9 1752.09     100 1749.52
   109.6 1745.47   119.2 1741.55   128.5 1739.54   128.9 1739.45   138.5 1739.32
   148.5 1740.19   167.4 1742.42     177 1743.15   205.9 1746.04   235.1 1748.77
   244.8 1749.78   254.5 1751.14   264.2 1752.72   293.3 1757.89     303 1759.29
   312.7 1760.44   322.4 1761.45   341.9 1763.44     371 1766.24
#Mann= 3 , 0 , 0
       0      .1       0   128.5    .045       0   148.5      .1       0
Bank Sta=128.5,148.5
XS Rating Curve= 0 ,0
Exp/Cntr=0.3,0.1

Type RM Length L Ch R = 1 ,8428.2  ,386,392.9,399.2
XS GIS Cut Line= 4
      1873662.83      375992.001     1873589.913      375898.251
     1873544.775      375825.334     1873504.844      375726.376
#Sta/Elev= 27
       0 1759.01     9.1 1758.26    36.5 1756.38    82.2 1753.38    91.4 1752.53
   100.5 1751.18   109.6 1749.49   118.8 1747.57   128.3 1745.51   137.8 1743.07
   147.4 1740.45   149.4 1740.01   156.9 1738.34   166.4 1738.14   169.4 1739.04
   175.9    1741   185.5 1745.26     195 1749.12   204.5 1752.06   214.2 1754.45
   223.9 1756.62   233.6  1758.5   243.3 1760.08     253 1761.51   262.7 1762.82
   282.1 1765.26   311.2  1768.5
#Mann= 3 , 0 , 0
       0      .1       0   149.4    .045       0   169.4      .1       0
Bank Sta=149.4,169.4
XS Rating Curve= 0 ,0
Exp/Cntr=0.3,0.1

Type RM Length L Ch R = 1 ,8035.2  ,185,186.3,187.5
XS GIS Cut Line= 4
     1873961.441      375875.681     1873931.927      375785.403
     1873900.677      375677.765     1873862.483      375584.015
#Sta/Elev= 22
       0 1750.35    66.5 1743.98      76 1742.99    85.5 1741.48      95 1739.22
   104.3 1736.46   113.7 1733.23   119.3 1731.68     123 1730.66   132.3 1729.65
   141.7  1729.9   169.7 1732.45   197.7 1734.74   207.1 1735.62   216.3 1737.42
   225.5 1740.17   234.7 1743.37   253.1 1749.98   262.3 1753.35   280.7 1760.24
   289.9 1763.77   308.3 1770.99
#Mann= 3 , 0 , 0
       0      .1       0   119.3    .045       0   141.7      .1       0
Bank Sta=119.3,141.7
XS Rating Curve= 0 ,0
Exp/Cntr=0.3,0.1

Type RM Length L Ch R = 1 ,7849    ,424,443.8,498.8
XS GIS Cut Line= 4
     1874084.705      375797.556     1874077.761      375684.709
     1874058.663      375604.848     1874046.511       375537.14
#Sta/Elev= 23
       0 1744.93     9.4 1743.18    18.8 1741.57    28.3 1740.19    37.7 1739.06
    56.5 1737.23    75.4 1735.54    84.8 1734.88   103.6 1733.96   113.1 1733.09
   122.2 1731.29   131.3 1728.49   136.9 1727.14   140.4  1726.3   149.6  1726.4
   156.9 1727.65   158.7 1727.96     186  1733.9   195.2 1736.25     205  1739.4
   214.8 1742.91   244.3 1753.78     264 1761.24
#Mann= 3 , 0 , 0
       0      .1       0   136.9    .045       0   156.9      .1       0
Bank Sta=136.9,156.9
XS Rating Curve= 0 ,0
Exp/Cntr=0.3,0.1

Type RM Length L Ch R = 1 ,7405.2  ,252.5,270.3,250.7
XS GIS Cut Line= 4
     1874352.066      375780.195     1874489.219      375669.084
     1874527.413      375490.265     1874515.261      375368.737
#Sta/Elev= 30
       0 1742.57     9.8 1741.46    39.2 1738.96      49 1737.55    58.8 1736.32
   117.7 1729.47   147.1  1725.9   156.9 1724.59   166.7 1723.53   176.5 1722.69
   186.1 1722.14   205.4  1720.6   221.1 1719.59   234.3 1718.98   241.1  1718.8
   272.8 1718.14   282.4 1718.03     292 1718.18   301.6 1718.76   311.2    1720
   320.9 1721.65   340.1 1725.15   359.4 1729.06   387.6    1736   396.9 1738.07
   406.3 1739.63   425.1 1742.02   434.5 1743.07   453.3 1744.76   481.5 1747.52
#Mann= 3 , 0 , 0
       0     .08       0   221.1    .045       0   241.1     .08       0
Bank Sta=221.1,241.1
XS Rating Curve= 0 ,0
Exp/Cntr=0.3,0.1

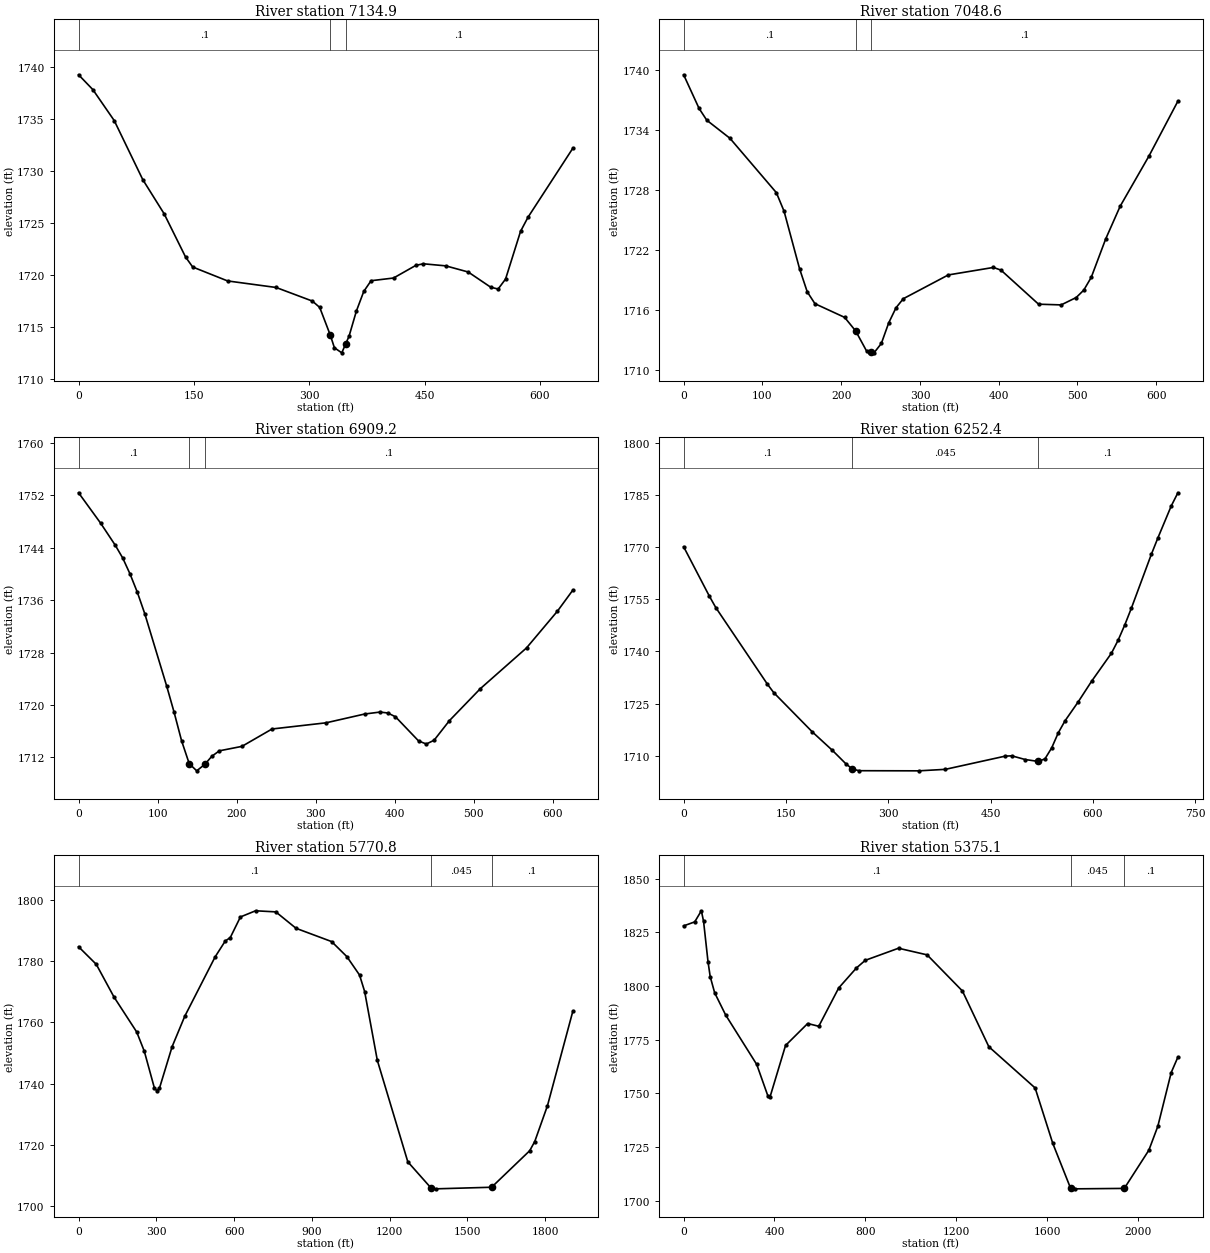
Type RM Length L Ch R = 1 ,7134.9  ,97.5,86.4,73.4
XS GIS Cut Line= 5
     1874449.288       375889.57     1874504.844      375742.001
     1874576.025      375660.403     1874681.927      375617.001
     1874671.511      375354.848
#Sta/Elev= 30
       0 1739.23    18.6  1737.8    46.4 1734.82    83.5 1729.14   111.3 1725.85
   139.1  1721.7   148.4 1720.73   193.8 1719.39   256.9 1718.76   304.1 1717.45
   313.6 1716.84   327.5 1714.15   332.7 1712.96   342.3 1712.47   347.5 1713.35
   351.8 1714.08   361.3 1716.49   370.9 1718.38   380.4 1719.41   409.6 1719.67
   438.7 1720.89   448.4 1721.04   477.6 1720.84   506.7 1720.25   535.9 1718.79
   545.6 1718.61   555.3 1719.57   574.8 1724.16   584.5 1725.52   642.8 1732.16
#Mann= 3 , 0 , 0
       0      .1       0   327.5    .045       0   347.5      .1       0
Bank Sta=327.5,347.5
XS Rating Curve= 0 ,0
Exp/Cntr=0.3,0.1

Type RM Length L Ch R = 1 ,7048.6  ,163.1,139.4,117.2
XS GIS Cut Line= 5
      1874506.58      375893.042     1874617.691       375755.89
     1874695.816      375676.028     1874702.761      375446.862
      1874725.33      375339.223
#Sta/Elev= 30
       0 1739.52    19.6 1736.15    29.4 1734.97    58.8 1733.16   117.7 1727.72
   127.5 1725.86   147.1 1720.12   156.9 1717.79   166.7  1716.6   204.4 1715.23
   218.4 1713.87   232.4 1711.84   238.4 1711.74   241.7 1711.68     251 1712.62
   260.3 1714.67   269.6 1716.19   278.9  1717.1     336 1719.48   393.3 1720.23
   402.9 1719.96   450.6 1716.55   479.3 1716.48   498.4 1717.22     508 1717.96
   517.5 1719.24   535.8 1723.08   554.2 1726.36   590.8 1731.39   627.5 1736.88
#Mann= 3 , 0 , 0
       0      .1       0   218.4    .045       0   238.4      .1       0
#XS Ineff= 2 , 0
                          336.34         1719.45
Permanent Ineff=
       F       F
Bank Sta=218.4,238.4
XS Rating Curve= 0 ,0
Exp/Cntr=0.3,0.1

Type RM Length L Ch R = 1 ,6909.2  ,657.6,656.9,655.3
XS GIS Cut Line= 4
     1874768.733      375967.695     1874742.691       375849.64
     1874718.386      375728.112     1874758.316       375349.64
#Sta/Elev= 30
       0 1752.35    27.9 1747.72    46.5 1744.34    55.8 1742.42    65.1 1739.98
    74.4 1737.17    83.7 1733.94   111.6 1722.84   120.9 1718.88   130.4 1714.52
     140 1711.06   149.5 1709.96     160 1710.98   168.6 1712.18   178.1 1713.01
   206.7 1713.69   244.8 1716.34   313.1 1717.28   361.9 1718.62   381.4 1718.92
   391.2 1718.78     401  1718.2   430.2 1714.52     440 1714.05   449.8 1714.62
   469.3 1717.62   508.3 1722.48   566.8  1728.7   605.9  1734.3   625.4 1737.51
#Mann= 3 , 0 , 0
       0      .1       0     140    .045       0     160      .1       0
#XS Ineff= 2 , 0
                          244.67         1716.23
Permanent Ineff=
       F       F
Bank Sta=140,160
XS Rating Curve= 0 ,0
Exp/Cntr=0.3,0.1

Type RM Length L Ch R = 1 ,6252.4  ,476.5,481.5,486.5
XS GIS Cut Line= 3
     1875282.622      375971.167     1875286.962      375782.365
     1875143.733      375265.872
#Sta/Elev= 30
       0 1770.12    37.8 1755.88    47.2 1752.61   122.8  1730.6   132.2 1728.14
   188.8 1716.84   218.1 1711.56   237.6 1707.75   247.3 1706.19   257.1  1705.7
   344.8 1705.66   383.8 1706.09   471.5 1709.89   481.2 1709.98   500.7 1708.92
   520.2 1708.36   529.9 1709.12   539.7 1712.26   549.4  1716.6   559.2 1720.03
   578.7 1725.53   598.2 1731.42   627.4 1739.52   637.1 1743.22   646.9 1747.64
   656.6 1752.47   685.9 1767.97   695.6 1772.74   715.1 1781.89   724.8 1785.65
#Mann= 3 , 0 , 0
       0      .1       0   247.3    .045       0   520.2      .1       0
Bank Sta=247.3,520.2
XS Rating Curve= 0 ,0
Exp/Cntr=0.3,0.1

Type RM Length L Ch R = 1 ,5770.8  ,397.8,395.8,393.4
XS GIS Cut Line= 4
     1875328.195      377008.494     1875473.594      376212.053
     1875705.799      375736.792     1875662.396      375170.386
#Sta/Elev= 30
       0 1784.68    68.3 1778.94   136.6 1768.27   224.4 1756.82   253.6 1750.54
   292.6  1738.5   302.4 1737.63   312.1 1738.49   360.9 1752.05   409.7 1761.99
   526.7 1781.36   565.8 1786.55   585.3 1787.69   624.3 1794.41   682.8 1796.43
   760.8 1796.07     839  1790.7   976.1 1786.37  1034.9 1781.46  1083.9 1775.43
  1103.5 1770.06  1152.4 1747.58    1270 1714.43  1358.2 1706.01  1377.7  1705.6
  1593.2 1706.12  1740.1 1718.04  1759.7 1721.06  1808.7 1732.75  1906.6 1763.62
#Mann= 3 , 0 , 0
       0      .1       0  1358.2    .045       0  1593.2      .1       0
Bank Sta=1358.2,1593.2
XS Rating Curve= 0 ,0
Exp/Cntr=0.3,0.1

Type RM Length L Ch R = 1 ,5375.1  ,777.4,767.2,755.1
XS GIS Cut Line= 4
     1876504.555      377272.817     1876246.049      376362.709
     1876113.785       375706.41     1876022.639      375153.025
#Sta/Elev= 30
       0 1828.04    48.8  1829.9      78 1835.07    87.8 1830.13   107.3 1811.37
     117 1804.41   136.6 1796.89   185.3 1786.49   321.9  1763.5   370.6 1748.97
   380.4 1748.39   448.7 1772.35   546.2 1782.58     595 1781.29   682.8 1799.13
   760.8 1808.44   799.8    1812   946.1 1817.63  1072.2 1814.54  1227.5 1797.73
  1343.9 1771.77  1547.7 1752.57  1625.4 1726.78  1704.2 1705.78  1723.8  1705.6
  1940.3  1705.8  2048.5 1723.59  2087.9  1734.7  2146.9 1759.75  2176.4 1766.95
#Mann= 3 , 0 , 0
       0      .1       0  1704.2    .045       0  1940.3      .1       0
Bank Sta=1704.2,1940.3
XS Rating Curve= 0 ,0
Exp/Cntr=0.3,0.1

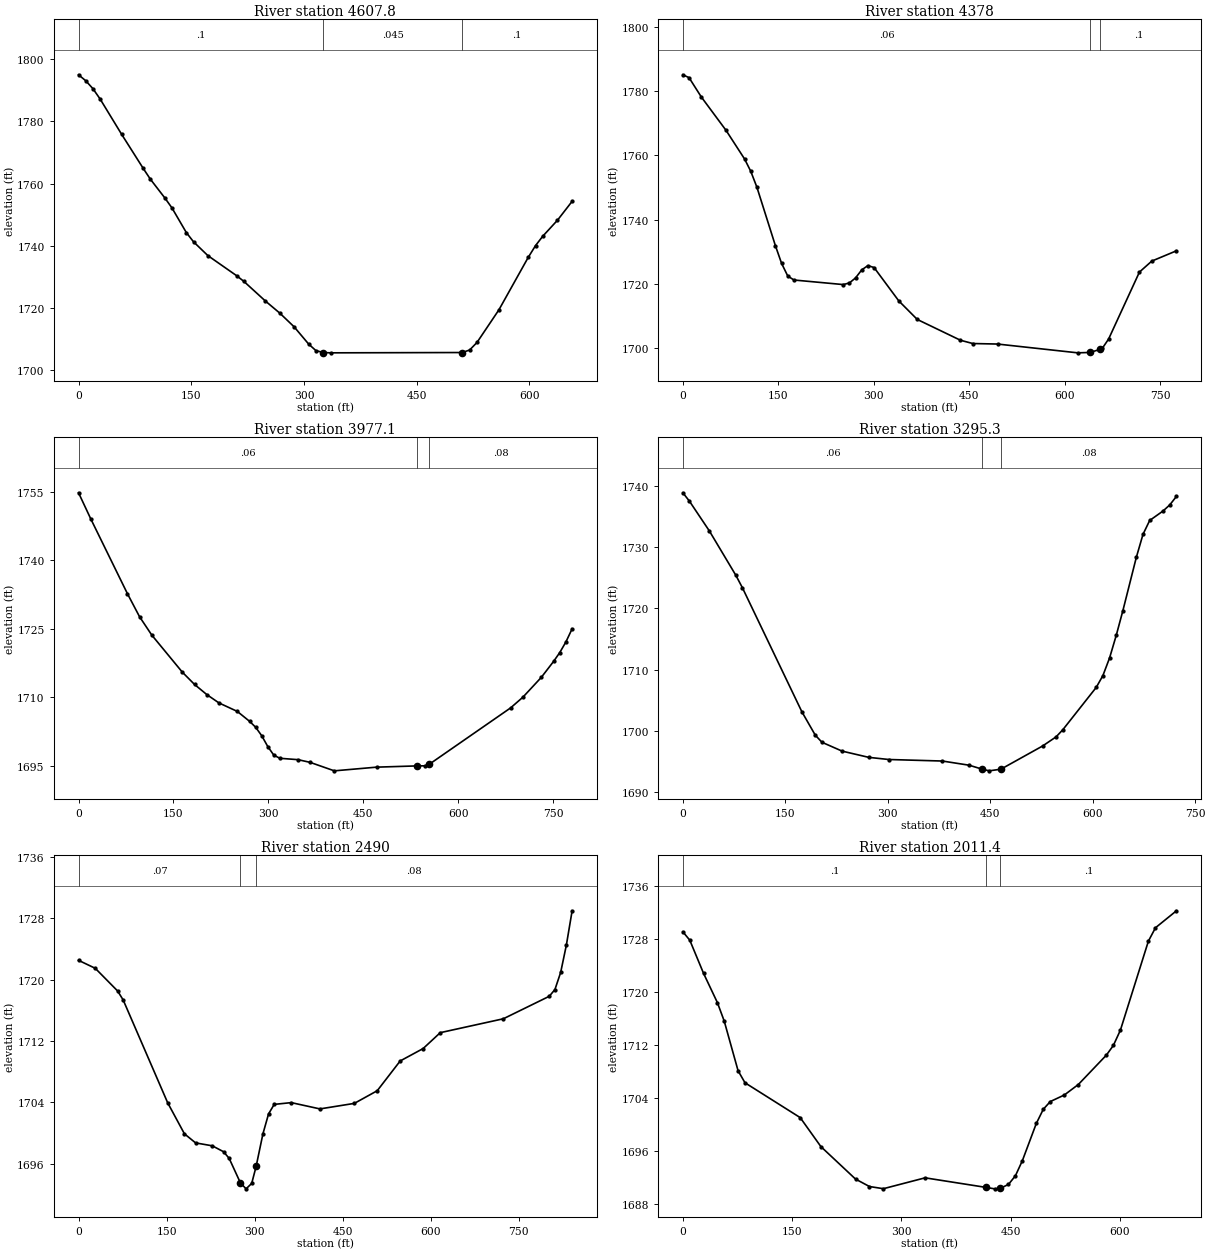
Type RM Length L Ch R = 1 ,4607.8  ,239.6,229.8,221.8
XS GIS Cut Line= 3
     1876962.309      375472.035     1876786.528       375233.32
     1876565.174      374949.032
#Sta/Elev= 30
       0 1794.94     9.6 1793.02    19.1 1790.49    28.7 1787.16    57.4 1775.79
    86.1 1764.85    95.6 1761.39   114.8 1755.38   124.3 1752.17   143.4 1744.26
     153 1741.28   172.1 1736.84   210.4 1730.38     220 1728.56   248.6 1722.26
   267.8 1718.36   286.9 1713.95   306.2 1708.42   315.9 1706.31   325.7  1705.7
   335.4  1705.6   510.7  1705.7   520.4 1706.51   530.2 1708.93   559.4 1719.43
   598.3 1736.24   608.1 1740.05   617.8 1743.09   637.3 1748.21   656.8 1754.28
#Mann= 3 , 0 , 0
       0      .1       0   325.7    .045       0   510.7      .1       0
Bank Sta=325.7,510.7
XS Rating Curve= 0 ,0
Exp/Cntr=0.3,0.1

Type RM Length L Ch R = 1 ,4378    ,388,400.9,413.1
XS GIS Cut Line= 3
     1877243.704      375332.134      1876966.65      375007.626
     1876680.191      374807.973
#Sta/Elev= 30
       0 1785.13     9.7 1784.24    29.1 1778.19    67.9 1767.81      97  1758.9
   106.7 1755.08   116.4  1750.1   145.5 1731.87   155.2 1726.37   164.9 1722.43
   174.6 1721.19   252.1 1719.77   261.8 1720.27   271.5 1721.85   281.2 1724.35
   290.9 1725.68   300.6 1725.07   339.4 1714.69   368.5  1708.9   436.4 1702.42
   455.8  1701.4   494.6 1701.24   620.7  1698.5   639.9 1698.62  656.07 1699.59
   659.5 1699.96   669.2 1702.78   717.7 1723.66   737.1 1727.08   775.9 1730.29
#Mann= 3 , 0 , 0
       0     .06       0   639.9    .045       0  656.07      .1       0
Bank Sta=639.9,656.07
XS Rating Curve= 0 ,0
Exp/Cntr=0.3,0.1

Type RM Length L Ch R = 1 ,3977.1  ,657.6,681.8,664.6
XS GIS Cut Line= 4
      1877339.19      375125.971     1877200.301      374882.915
     1877050.562      374583.436     1876948.565      374453.227
#Sta/Elev= 30
       0 1754.84    19.3 1749.13    77.2 1732.75    96.5 1727.66   115.8 1723.65
   164.1 1715.52   183.4 1712.83   202.7 1710.62     222 1708.78     251 1706.92
   270.3 1704.76   279.9 1703.46   289.5 1701.61   299.1 1699.23   308.6 1697.35
   318.2 1696.65   346.9 1696.35     366 1695.76   404.3  1693.9   471.3 1694.71
   534.7 1694.98   547.8    1695   554.7 1695.37   682.9 1707.69   702.3 1710.03
   731.5 1714.39     751  1717.9   760.7 1719.83   770.4 1722.16   780.2 1725.03
#Mann= 3 , 0 , 0
       0     .06       0   534.7    .045       0   554.7     .08       0
Bank Sta=534.7,554.7
XS Rating Curve= 0 ,0
Exp/Cntr=0.3,0.1

Type RM Length L Ch R = 1 ,3295.3  ,820.2,805.3,789.6
XS GIS Cut Line= 3
      1877810.11      374902.446     1877753.687      374737.516
     1877504.121      374249.234
#Sta/Elev= 30
       0 1738.88     9.7  1737.5    38.7 1732.67    77.5 1725.43    87.2 1723.38
   174.3 1703.13   193.9 1699.32   203.7 1698.16   233.1 1696.72   272.2  1695.7
   301.6 1695.35     380  1695.1   419.1 1694.42   438.7 1693.76   448.5  1693.5
   465.7 1693.77   526.8 1697.56   546.4 1699.04   556.2 1700.19   605.2 1707.11
     615 1709.04   624.8 1711.93   634.6 1715.63   644.3 1719.66   663.9 1728.32
   673.7 1732.09   683.5 1734.36   703.1 1735.91   712.9  1736.9   722.7 1738.29
#Mann= 3 , 0 , 0
       0     .06       0   438.7    .045       0   465.7     .08       0
Bank Sta=438.7,465.7
XS Rating Curve= 0 ,0
Exp/Cntr=0.3,0.1

Type RM Length L Ch R = 1 ,2490    ,445.5,478.6,512.2
XS GIS Cut Line= 4
      1878439.45      374739.686     1878370.006      374522.672
      1878272.35      374461.908     1878155.162      373977.967
#Sta/Elev= 30
       0  1722.5    28.5 1721.46    66.5 1718.51      76 1717.34   151.9 1703.92
   180.4 1699.88   199.4  1698.7   227.8 1698.32     247 1697.55   256.6 1696.68
   275.8 1693.48   285.4 1692.71     295 1693.42   302.5 1695.63   314.1 1699.88
   323.7 1702.48   333.3 1703.72   362.4 1703.95   411.2 1703.13   469.8 1703.85
   508.8  1705.5   547.9 1709.38     587    1711   616.2 1713.07   723.6 1714.88
   801.8 1717.81   811.5 1718.69   821.3 1720.93     831 1724.49   840.8 1728.96
#Mann= 3 , 0 , 0
       0     .07       0   275.8    .045       0   302.5     .08       0
Bank Sta=275.8,302.5
XS Rating Curve= 0 ,0
Exp/Cntr=0.3,0.1

Type RM Length L Ch R = 1 ,2011.4  ,182.2,185.1,187
XS GIS Cut Line= 4
       1878595.7      374726.665     1878643.443      374533.523
     1878712.888      374255.745     1878689.016      374064.773
#Sta/Elev= 30
       0 1729.11     9.5 1727.85    28.4 1722.85    47.4 1718.44    56.8 1715.65
    75.8 1708.17    85.3 1706.35   161.1  1701.1   189.5 1696.73   237.1 1691.83
   256.2 1690.71   275.3 1690.38   332.6 1692.02   416.1 1690.58     428 1690.36
   436.1 1690.45   447.1 1691.03   456.6 1692.33   466.2 1694.62   485.3 1700.22
   494.9 1702.36   504.5 1703.52   523.8 1704.51     543 1706.09   581.5 1710.52
   591.1 1711.98   600.8  1714.3   639.2 1727.71   648.9 1729.72   677.7 1732.28
#Mann= 3 , 0 , 0
       0      .1       0   416.1    .045       0   436.1      .1       0
Bank Sta=416.1,436.1
XS Rating Curve= 0 ,0
Exp/Cntr=0.3,0.1

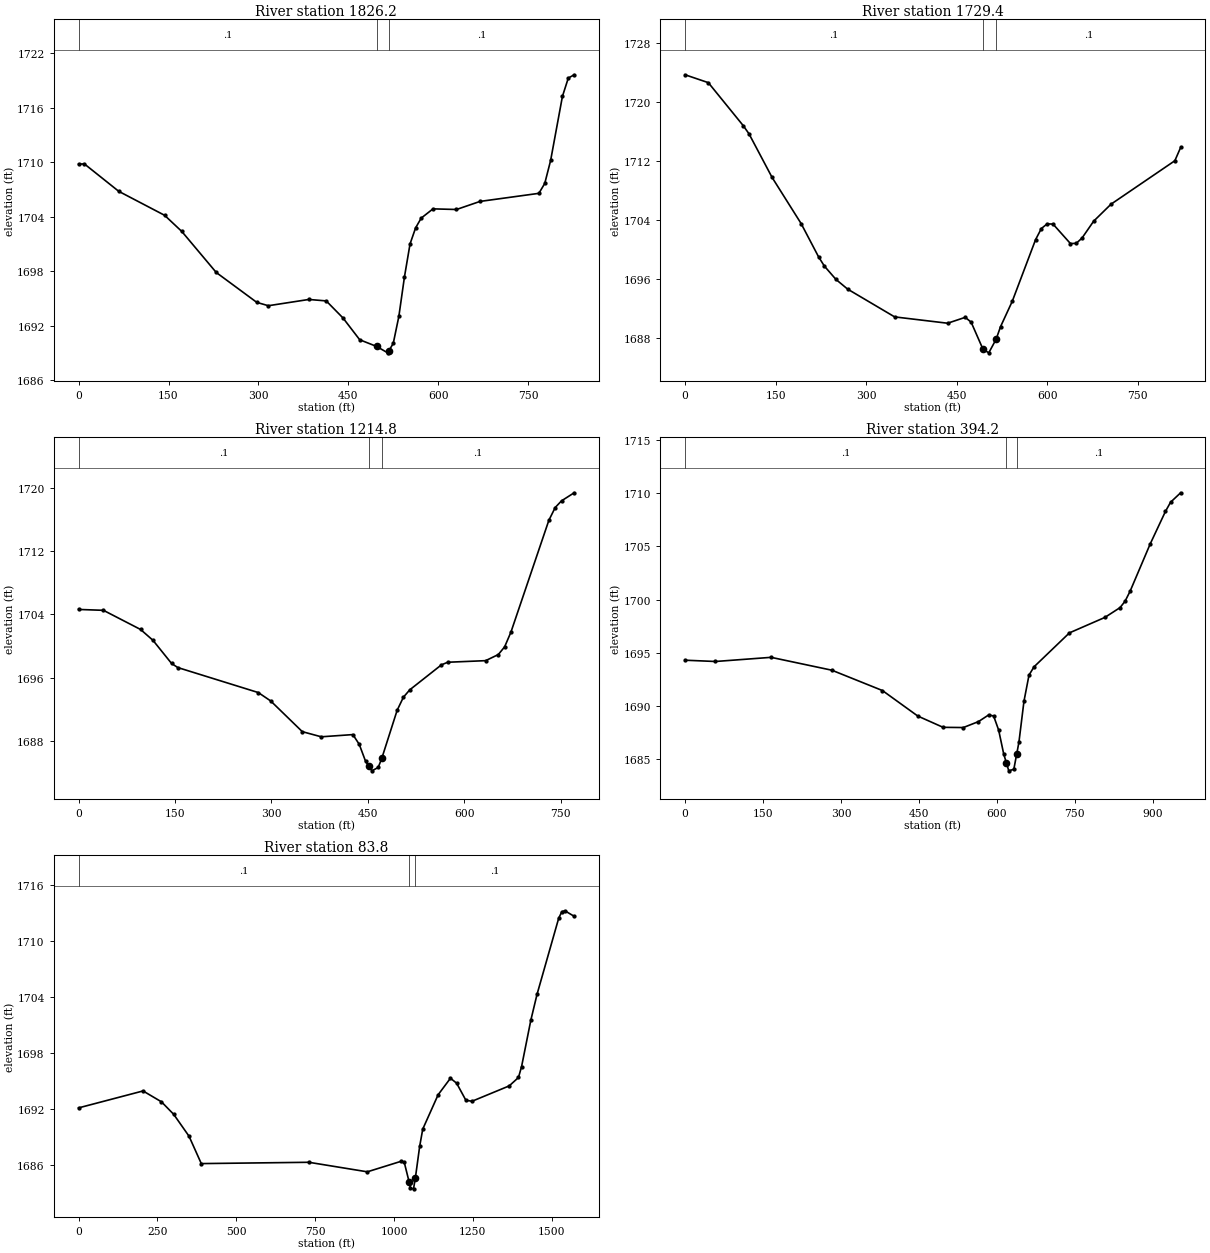
Type RM Length L Ch R = 1 ,1826.2  ,96.7,96.8,97.5
XS GIS Cut Line= 5
     1878710.718      374770.068     1878767.141      374557.394
     1878856.117      374385.953     1878893.443      374231.873
     1878899.954      373976.665
#Sta/Elev= 30
       0 1709.79     9.6 1709.81      67 1706.79   143.5 1704.15   172.2 1702.37
   229.7 1697.85   297.3 1694.56   316.6 1694.19   384.2 1694.88   413.2 1694.72
   441.2 1692.84   469.1 1690.44   497.5  1689.7   515.8    1689   517.5 1689.19
   525.1 1690.05   534.4 1693.01   543.8 1697.38   553.1    1701   562.4 1702.77
   571.7 1703.84   591.4 1704.86   630.6 1704.79   669.9 1705.68   768.1 1706.57
   777.9 1707.66   787.7 1710.19   807.4 1717.25   817.2 1719.27     827 1719.63
#Mann= 3 , 0 , 0
       0      .1       0   497.5    .045       0   517.5      .1       0
Bank Sta=497.5,517.5
XS Rating Curve= 0 ,0
Exp/Cntr=0.3,0.1

Type RM Length L Ch R = 1 ,1729.4  ,526,514.6,502.2
XS GIS Cut Line= 4
     1878823.131      374777.446     1878888.235      374526.144
     1878988.496      374251.405     1879023.652      373984.477
#Sta/Elev= 30
       0 1723.74    38.5 1722.67    96.2 1716.85   105.8 1715.74   144.2  1709.8
   192.3 1703.54   221.1 1699.04   230.8 1697.77     250 1695.96   269.4 1694.64
   347.3 1690.87   435.1 1690.01   464.3 1690.81   474.1 1690.15   493.6  1686.5
   503.3 1685.99   515.5 1687.84   522.8 1689.54   542.3    1693   580.9 1701.36
   590.5 1702.87   600.1  1703.5   609.8 1703.47   638.6 1700.83   648.2 1700.85
   657.8 1701.57   677.1 1703.86   705.9 1706.17   811.7 1712.07   821.3 1713.87
#Mann= 3 , 0 , 0
       0      .1       0   493.6    .045       0   515.5      .1       0
Bank Sta=493.6,515.5
XS Rating Curve= 0 ,0
Exp/Cntr=0.3,0.1

Type RM Length L Ch R = 1 ,1214.8  ,826.2,820.6,814.4
XS GIS Cut Line= 3
     1879410.371      374743.592     1879504.121      374459.738
     1879446.829      373990.988
#Sta/Elev= 30
       0 1704.62    38.6 1704.51    96.4 1702.09   115.7 1700.72   144.6  1697.8
   154.3 1697.28   279.6 1694.12   298.9 1693.06   348.1 1689.18   377.6 1688.53
   426.8 1688.81   436.7 1687.58   446.5 1685.45   451.8  1684.8   456.4 1684.23
   466.2 1684.66   471.8 1685.81   495.7 1691.88   505.5 1693.54   515.4 1694.47
   564.6 1697.62   574.4 1697.95   633.4 1698.15   653.1 1698.92     663  1699.9
   672.8 1701.76   731.8 1715.88   741.7  1717.5   751.5 1718.34   771.2 1719.36
#Mann= 3 , 0 , 0
       0      .1       0   451.8    .045       0   471.8      .1       0
Bank Sta=451.8,471.8
XS Rating Curve= 0 ,0
Exp/Cntr=0.3,0.1

Type RM Length L Ch R = 1 ,394.2   ,309.3,310.4,311.7
XS GIS Cut Line= 3
     1880274.954       374530.05     1880267.141      374121.196
     1880077.037       373610.78
#Sta/Elev= 30
       0  1694.3    58.4 1694.18   165.5 1694.57   282.4 1693.36   379.7 1691.45
   447.8 1689.05   496.5 1687.99   535.4 1687.97   564.6 1688.53     584 1689.15
   593.7 1689.06   603.4 1687.73   613.2 1685.47   618.2 1684.66   622.9  1683.9
   632.6 1684.05   638.2  1685.5   642.4 1686.59   652.1 1690.44   661.8  1692.9
   671.5 1693.68   739.6 1696.87   807.7 1698.32   836.9 1699.24   846.6 1699.84
   856.3 1700.78   895.2 1705.25   924.4 1708.29   934.2 1709.15   953.6 1710.04
#Mann= 3 , 0 , 0
       0      .1       0   618.2    .045       0   638.2      .1       0
Bank Sta=618.2,638.2
XS Rating Curve= 0 ,0
Exp/Cntr=0.3,0.1

Type RM Length L Ch R = 1 ,83.8    ,82,83.8,85.7
XS GIS Cut Line= 4
     1880470.266      374787.863     1880652.558      374347.759
     1880439.016      373678.488     1880108.287       373467.55
#Sta/Elev= 30
       0 1692.11   204.2 1693.92   262.5 1692.76   301.4 1691.42     350 1689.08
   388.9 1686.15     730 1686.29   915.4 1685.27  1022.8  1686.4  1032.5 1686.28
  1047.8  1684.2    1052 1683.51  1061.8 1683.45  1067.8 1684.64  1081.3 1687.99
  1091.1 1689.84  1139.8 1693.51  1178.9 1695.28  1198.5 1694.75  1227.9 1692.92
  1247.5 1692.82  1365.2 1694.46  1394.6 1695.36  1404.4 1696.52  1433.8 1701.49
  1453.5 1704.26  1522.1 1712.39  1531.9 1713.08  1541.7 1713.19  1571.2  1712.6
#Mann= 3 , 0 , 0
       0      .1       0  1047.8    .045       0  1067.8      .1       0
Bank Sta=1047.8,1067.8
XS Rating Curve= 0 ,0
Exp/Cntr=0.3,0.1

Chan Stop Cuts=-1
Use User Specified Reach Order=0
Composite Channel Slope=5